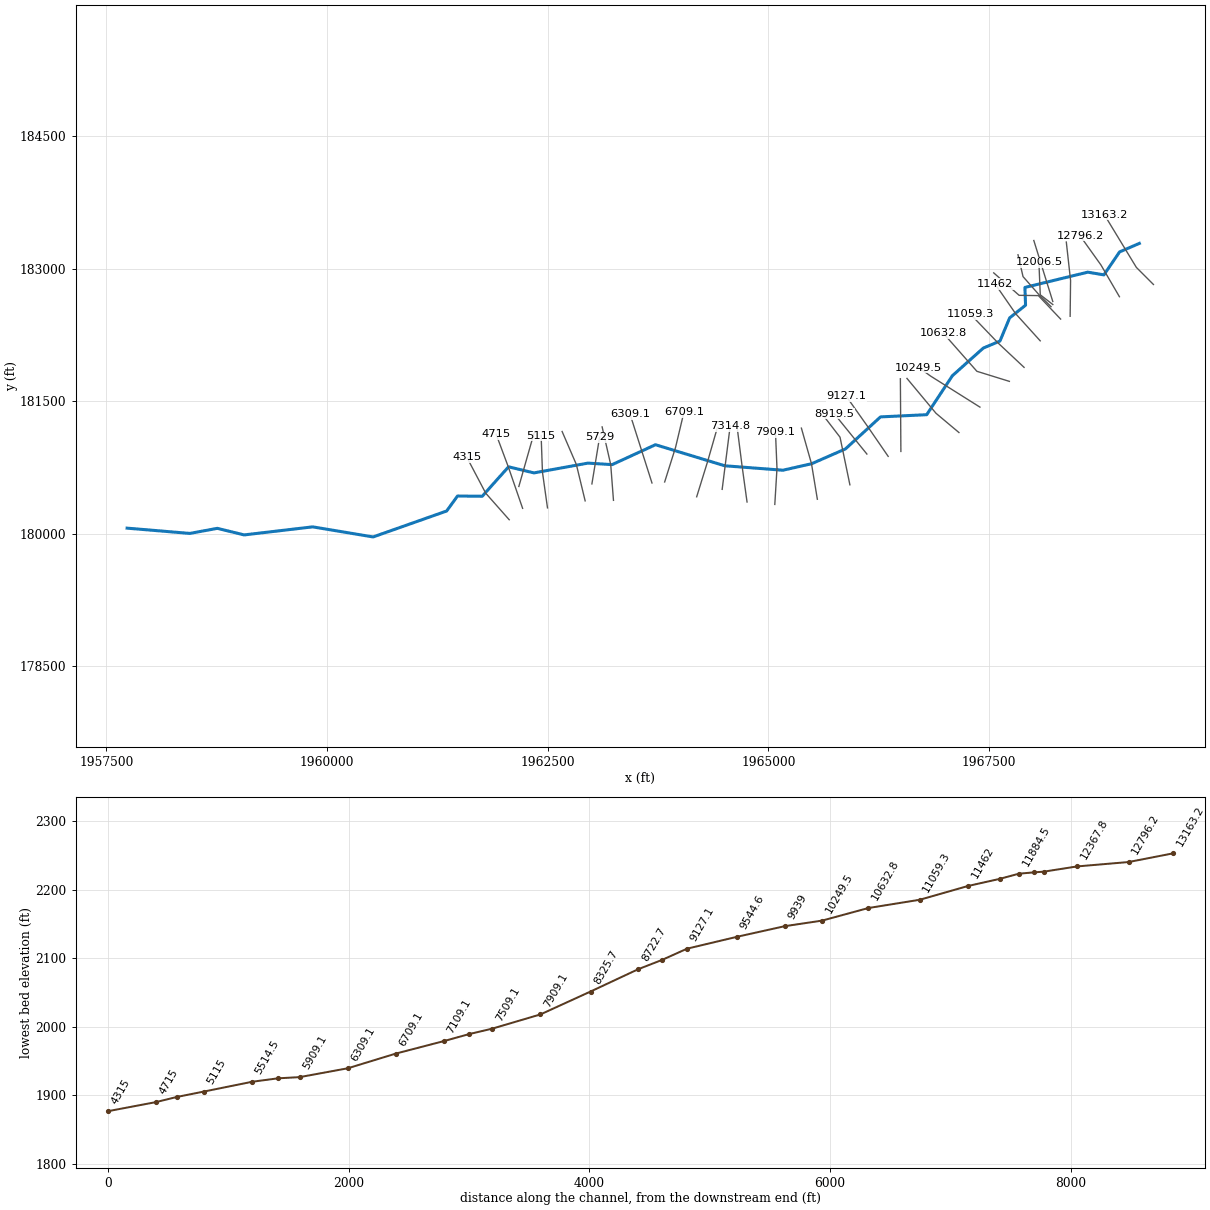
--- IndnBrnch.prj (project) ---

Proj Title=IndnBrnch
Current Plan=p01
Default Exp/Contr=0,0
English Units
Geom File=g01
Flow File=f01
Plan File=p01
BEGIN DESCRIPTION:
END DESCRIPTION:
DSS Export Rating Curves= 0
DSS Export Rating Curve Sorted= 0
DSS Export Volume Flow Curves= 0
DXF OffsetX= 0
DXF OffsetY= 0
DXF ScaleX= 0
DXF ScaleY= 0

--- IndnBrnch.p01 (plan) ---

Plan Title=Floodplain
Program Version=4.00
Geom File=g01
Flow File=f01
K Sum by GR=0
Std Step Tol=0.01
Critical Tol=0.01
Num of Std Step Trials=20
Max Error Tol=0.3
Flow Tol Ratio=0.001
Split Flow NTrial=30
Split Flow Tol=0.02
Split Flow Ratio=0.02
Log Output Level=0
Friction Slope Method=1
Unsteady Friction Slope Method=2
Unsteady Bridges Friction Slope Method=1
Global Log Level=0
CheckData=False
Run HTab=0
Run UNet=0
Run PostProcess=0
UNET Theta=0
UNET Theta Warmup=0
UNET ZTol=0
UNET ZSATol=0
UNET MxIter=0
UNET MaxInSteps=0
UNET DtIC=0
UNET DtMin=0
UNET MaxCRTS=0
UNET WFStab=0
UNET SFStab=0
UNET WFX=0
UNET SFX=0
UNET DSS MLevel=0
UNET DZMax Abort=0
UNET Convert EG Bridges=0
UNET Use Existing IB Tables=0
UNET Froude Limit=0
UNET Froude Power=0
Write IC File=0
Echo Input=False
Echo Output=False
Write Detailed=0

--- IndnBrnch.f01 (steady flow) ---

Flow Title=NFF Regression Equation
Program Version=4.00
Number of Profiles=1
Profile Names=P100yr
River Rch & RM=IndnBrnch,Main      ,13163.2
535.6406
River Rch & RM=IndnBrnch,Main      ,11059.3
551.9811
River Rch & RM=IndnBrnch,Main      ,10632.8
612.2292
River Rch & RM=IndnBrnch,Main      ,9939
676.8351
River Rch & RM=IndnBrnch,Main      ,7909.1
705.6902
River Rch & RM=IndnBrnch,Main      ,7509.1
803.5632
River Rch & RM=IndnBrnch,Main      ,5729
840.4063
River Rch & RM=IndnBrnch,Main      ,4715
929.0329
River Rch & RM=IndnBrnch,Main      ,2627.2
948.6341
River Rch & RM=IndnBrnch,Main      ,2292.6
1213.661
River Rch & RM=IndnBrnch,Main      ,440.8
1250.289
Boundary for River Rch & Prof#=IndnBrnch,Main      ,1
Up Type=0
Dn Type=3
Dn Slope=0.052082

--- IndnBrnch.g01 (geometry) ---

Geom Title=USGS 3m DEM
Program Version=4.10

River Reach=IndnBrnch       ,Main
Reach XY= 30
     1969201.142      183285.047     1968977.188       183188.73
     1968799.949      182928.716     1968617.683      182959.488
     1967905.187       182786.69     1967912.132      182585.018
     1967731.693      182441.203     1967622.294      182179.726
     1967433.492      182100.299     1967083.804      181787.775
     1966792.575      181346.335     1966269.523      181321.457
     1965872.295      180959.024     1965490.133      180791.705
     1965164.088      180717.847     1964504.455      180768.268
     1963720.601      181006.549     1963229.716      180781.288
     1962955.587      180798.328     1962344.299      180687.539
     1962056.539      180756.549     1961758.362      180423.216
     1961478.414       180425.82     1961355.429      180256.263
     1960522.211      179962.743     1959837.789      180076.861
     1959061.747      179985.715     1958758.362      180059.934
     1958445.862      180002.643      1957736.15      180062.333

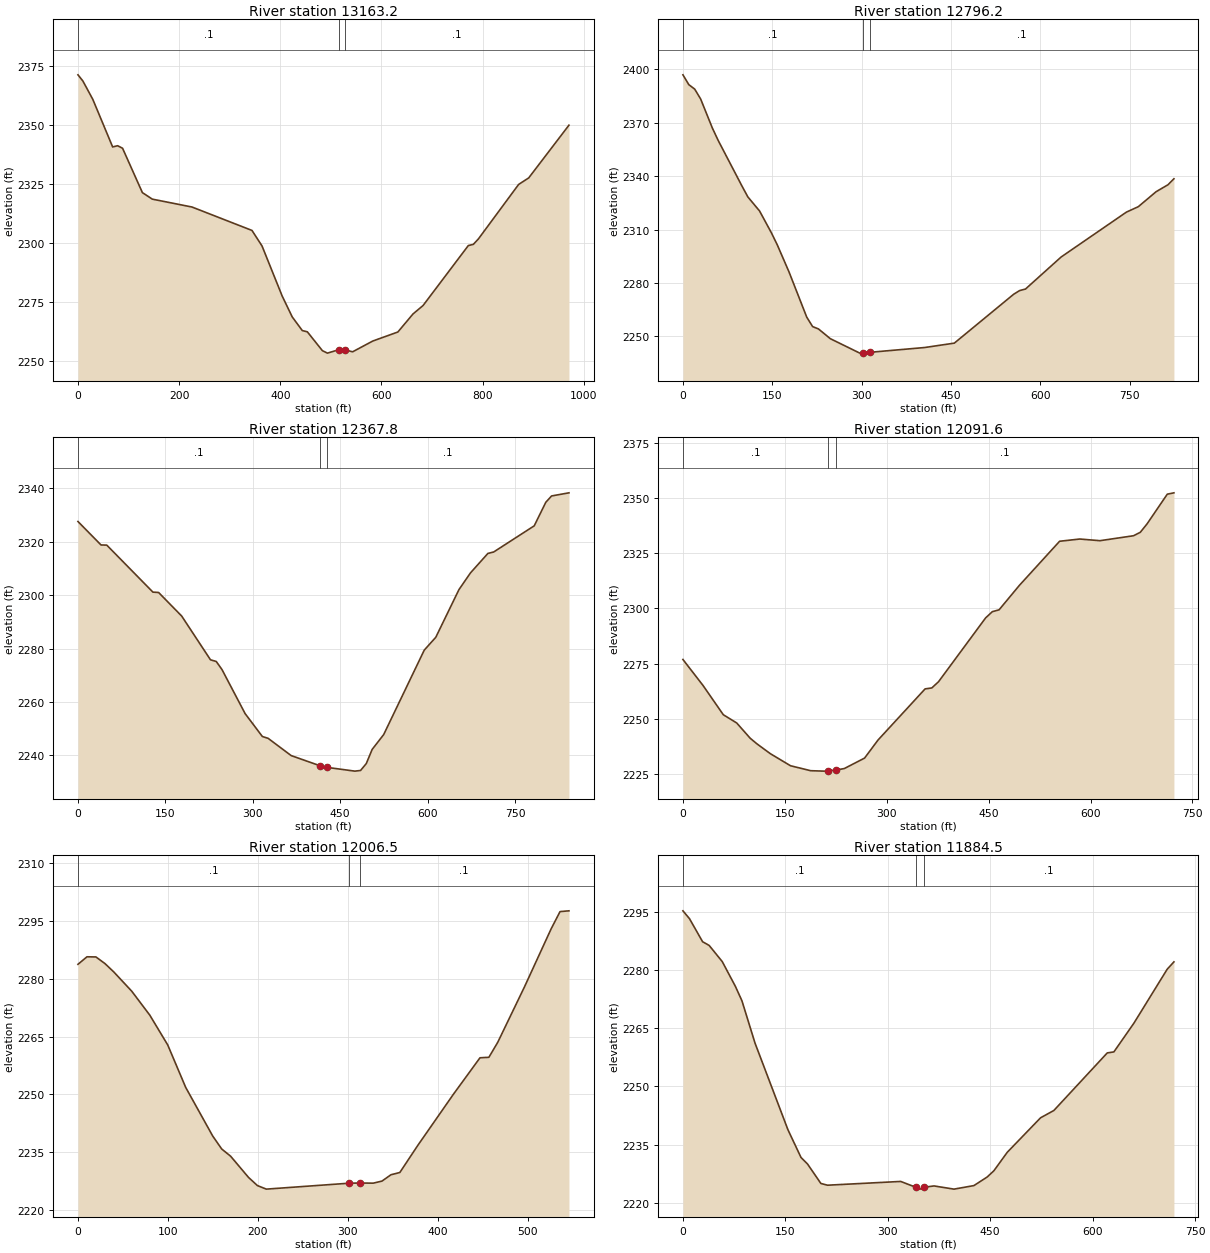
Type RM Length L Ch R = 1 ,13163.2 ,366.8,366.6,366.4
XS GIS Cut Line= 3
     1969360.951      182819.829     1969166.849      183013.931
     1968805.133      183609.004
#Sta/Elev= 30
       0 2371.42     9.8 2368.77    29.4 2360.97    68.6 2340.77    78.4 2341.29
    88.2 2340.22   127.4 2321.36     147 2318.59   225.5 2315.24   344.1 2305.29
     364 2298.68   403.8 2277.42   423.7 2268.53   443.6 2262.74   453.6  2262.2
   483.4 2254.18   493.4 2253.15   516.8 2254.68   528.8 2254.48   543.1 2253.71
   582.9 2258.28   632.6 2262.13   662.5 2269.79   682.4 2273.38   771.9 2298.86
   781.9 2299.39   791.8 2301.67   871.4 2324.84   891.3 2327.61   970.9 2350.02
#Mann= 3 , 0 , 0
       0      .1       0   516.8    .045       0   528.8      .1       0
Bank Sta=516.8,528.8
XS Rating Curve= 0 ,0
Exp/Cntr=0.3,0.1

Type RM Length L Ch R = 1 ,12796.2 ,438.1,428.3,419.2
XS GIS Cut Line= 3
     1968975.437       182681.43     1968766.177      183040.552
     1968528.568      183372.735
#Sta/Elev= 30
       0 2396.87     9.9 2391.34    19.8 2388.84    29.7 2383.32    49.5  2366.9
    59.4 2359.88      99 2334.47   108.9 2328.34   128.6 2320.41   148.4 2308.21
   158.3 2301.42   178.1 2286.15   207.8 2260.78   217.7 2255.47   227.6 2254.13
   247.4 2248.68   296.9 2240.57   302.2 2240.61   314.2 2241.04   405.8 2243.72
   455.5 2246.18   555.1 2273.63   565.1  2275.7     575 2276.57   634.8 2294.56
   744.4 2319.77   764.3 2322.81   794.2 2331.23   814.1 2335.12   824.1 2338.49
#Mann= 3 , 0 , 0
       0      .1       0   302.2    .045       0   314.2      .1       0
Bank Sta=302.2,314.2
XS Rating Curve= 0 ,0
Exp/Cntr=0.3,0.1

Type RM Length L Ch R = 1 ,12367.8 ,272,276.2,279.8
XS GIS Cut Line= 3
     1968417.192      182460.308     1968422.116       182865.71
     1968373.833      183300.115
#Sta/Elev= 30
       0 2327.54    39.6 2318.76    49.4 2318.72   128.6 2301.12   138.4 2300.98
     178 2292.16   227.4 2275.79   237.3 2275.16   247.2 2272.12   286.8 2255.66
   316.4 2247.09   326.3  2246.4   365.9 2239.94   415.6 2236.12   427.6 2235.53
     475 2234.13   484.9 2234.37   494.8 2236.98   504.8 2242.25   524.6 2247.81
   594.2 2279.41     614 2284.22   653.8 2302.08   673.6 2308.34   703.4  2315.6
   713.4 2316.15   782.9 2325.93   802.8 2334.75   812.7 2337.11   842.5 2338.28
#Mann= 3 , 0 , 0
       0      .1       0   415.6    .045       0   427.6      .1       0
Bank Sta=415.6,427.6
XS Rating Curve= 0 ,0
Exp/Cntr=0.3,0.1

Type RM Length L Ch R = 1 ,12091.6 ,90.6,85.1,79.5
XS GIS Cut Line= 2
     1968220.759      182627.448     1968005.841      183317.606
#Sta/Elev= 30
       0 2276.95    29.7 2265.16    59.4    2252    79.2 2248.25      99 2241.37
   108.9 2238.84   128.7 2234.38   158.4 2228.93   188.1 2226.69   207.9  2226.5
   213.7 2226.61   225.7 2227.01   237.6 2227.67   267.4 2232.39   287.2 2240.55
   356.5 2263.66   366.4 2264.09   376.3 2266.91   445.6 2295.74   455.5 2298.56
   465.4 2299.39   495.1 2310.37   554.5 2330.37   584.2 2331.38   613.9 2330.63
   663.4 2332.87   673.3 2334.43   683.2  2338.2     713 2351.64   722.8 2352.26
#Mann= 3 , 0 , 0
       0      .1       0   213.7    .045       0   225.7      .1       0
Bank Sta=213.7,225.7
XS Rating Curve= 0 ,0
Exp/Cntr=0.3,0.1

Type RM Length L Ch R = 1 ,12006.5 ,106.9,122,137.1
XS GIS Cut Line= 3
     1968220.977      182593.065     1968078.922      182703.158
     1968063.532      183068.949
#Sta/Elev= 30
       0 2283.79      10 2285.74      20  2285.7      30 2283.98    39.9 2281.79
    59.9 2276.77    79.9 2270.57    99.8 2262.84   119.8  2251.8   149.8 2239.19
   159.8 2235.82   169.7 2233.95   189.6 2228.44   199.5 2226.32   209.4  2225.4
     301 2226.93     313 2226.99   328.2 2226.95     338 2227.49   347.9 2229.13
   357.8 2229.72   377.6  2236.7   417.2 2249.99   446.9 2259.51   456.8 2259.64
   466.7 2263.56   496.4 2277.95     526    2293   535.9 2297.48   545.8 2297.68
#Mann= 3 , 0 , 0
       0      .1       0     301    .045       0     313      .1       0
Bank Sta=301,313
XS Rating Curve= 0 ,0
Exp/Cntr=0.3,0.1

Type RM Length L Ch R = 1 ,11884.5 ,142.8,161,179.2
XS GIS Cut Line= 4
     1968200.852      182569.389     1968070.635      182697.239
     1967883.596      182909.137     1967826.774       183156.55
#Sta/Elev= 30
       0 2295.21     9.6 2293.19    28.8 2287.25    38.4  2286.3    57.6 2282.13
    76.8 2275.76    86.4 2272.04   105.6 2261.12   153.7 2238.85   172.9 2231.68
   182.5 2229.98     202 2224.98   211.7 2224.53   318.9  2225.5   341.3 2223.98
   348.2 2223.54   353.3 2224.01   367.7 2224.34   396.9 2223.52   426.1 2224.43
   445.6 2226.65   455.4 2228.26   474.9    2233   523.7 2241.89   543.2 2243.78
   621.4 2258.61   631.1 2258.87   660.4 2266.27   709.2 2280.18     719 2282.06
#Mann= 3 , 0 , 0
       0      .1       0   341.3    .045       0   353.3      .1       0
Bank Sta=341.3,353.3
XS Rating Curve= 0 ,0
Exp/Cntr=0.3,0.1

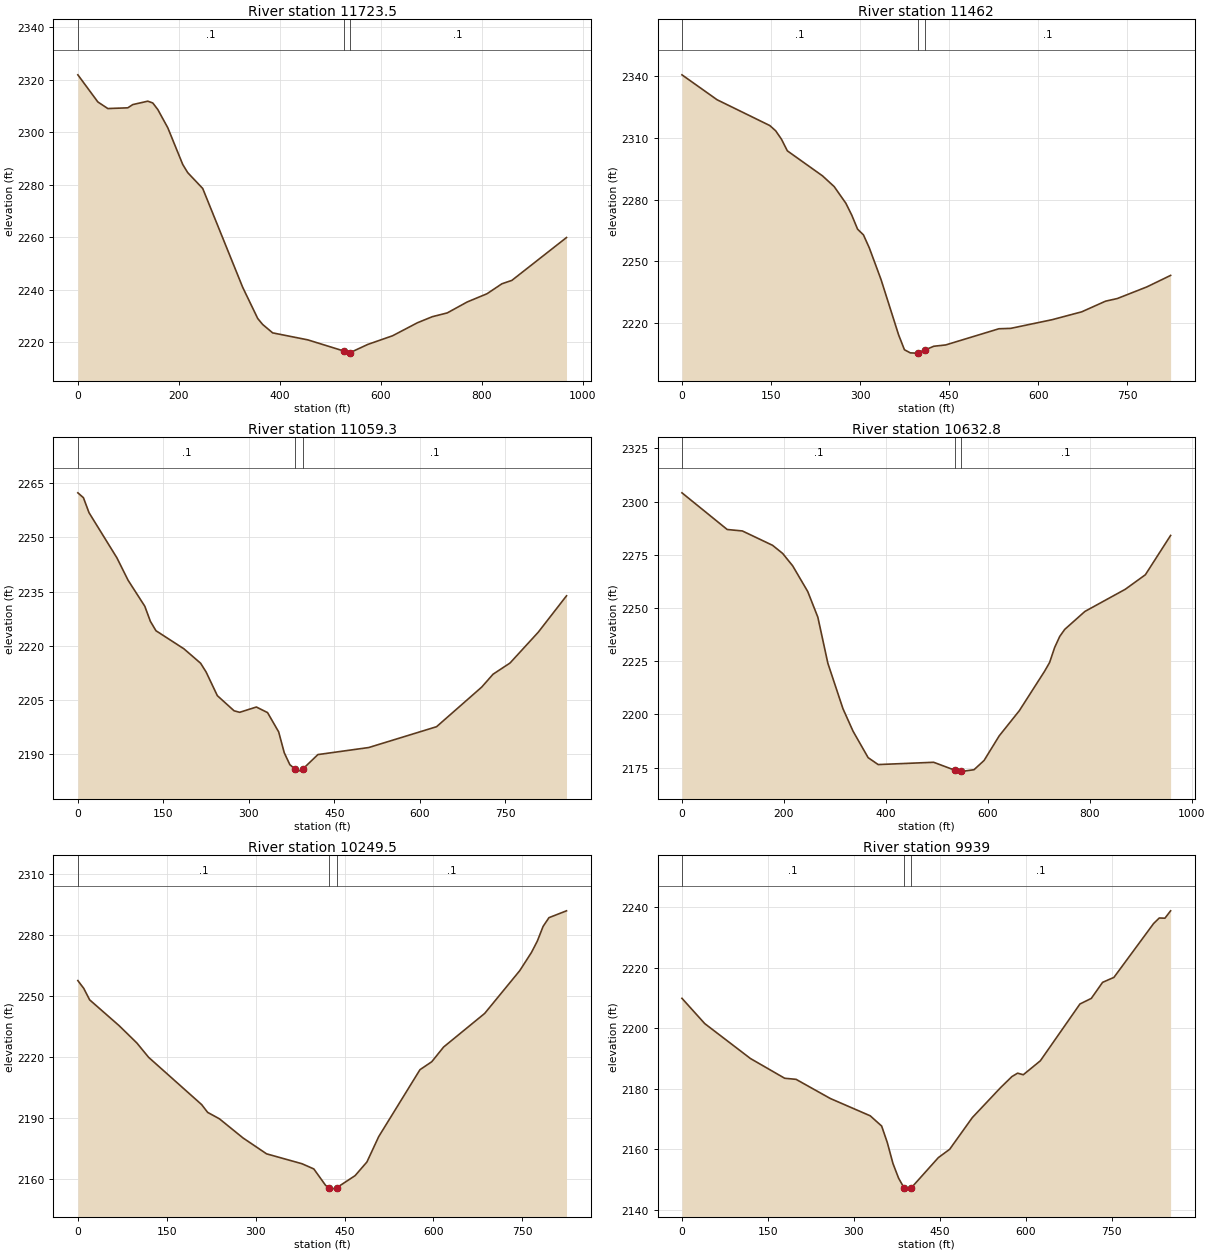
Type RM Length L Ch R = 1 ,11723.5 ,279.8,261.4,241.8
XS GIS Cut Line= 4
     1968309.308      182428.568       1968057.3      182694.042
     1967839.403      182697.246      1967551.79      182951.338
#Sta/Elev= 30
       0 2321.82    39.6  2311.5    59.4 2308.98    98.9 2309.26   108.8 2310.49
   138.5 2311.79   148.4  2311.1   158.3 2308.62   178.1 2301.68   207.8 2287.66
   217.6 2284.58   247.3 2278.55   326.5 2240.91   356.2 2229.07     366 2226.79
   385.8 2223.59   455.2 2220.94   526.2 2216.71   534.4 2215.88   538.2 2215.98
     574 2219.18   623.3 2222.49   672.5 2227.44     702 2229.75   731.6 2231.19
   770.9 2235.34   810.3 2238.49   839.8 2242.28   859.5 2243.57   967.7 2259.88
#Mann= 3 , 0 , 0
       0      .1       0   526.2    .045       0   538.2      .1       0
Bank Sta=526.2,538.2
XS Rating Curve= 0 ,0
Exp/Cntr=0.3,0.1

Type RM Length L Ch R = 1 ,11462   ,400.4,402,404
XS GIS Cut Line= 3
     1968078.228      182182.314     1967800.119      182489.215
     1967567.526      182825.439
#Sta/Elev= 30
       0 2340.43    59.2 2328.35   147.9 2315.86   157.8 2313.33   167.6 2309.24
   177.5  2303.6   236.7 2291.48   256.4 2286.27   276.1 2278.19     286 2272.45
   295.8 2265.65   305.7 2262.87   315.6 2256.55   335.3 2241.24   364.9 2214.44
   374.7 2207.23   384.6  2205.7   394.4 2205.58   396.9 2205.79   408.9 2207.06
   424.1 2208.91   444.1 2209.54   533.8 2217.38   553.8 2217.58   623.6 2221.79
   673.4  2225.6   713.3 2230.74   733.3 2232.04   783.1 2237.68     823 2243.24
#Mann= 3 , 0 , 0
       0      .1       0   396.9    .045       0   408.9      .1       0
Bank Sta=396.9,408.9
XS Rating Curve= 0 ,0
Exp/Cntr=0.3,0.1

Type RM Length L Ch R = 1 ,11059.3 ,428.6,426.6,425.5
XS GIS Cut Line= 3
     1967895.504      181881.982     1967602.698      182156.224
     1967286.878      182484.839
#Sta/Elev= 30
       0 2262.29     9.8 2260.94    19.6  2256.8    68.5 2244.33    88.1 2238.14
   117.4 2230.96   127.2 2226.79     137 2224.19   185.9 2219.21   215.3 2215.21
     225 2212.77   244.6 2206.26     274 2202.07   283.8 2201.65   313.1 2203.11
   332.7 2201.57   352.2 2196.24     362 2190.48   371.8 2187.19   381.6 2185.87
   391.4  2185.4   395.2 2186.08     421 2189.97   510.2 2191.92   629.1 2197.67
   708.3 2208.62   728.2 2212.18   757.9 2215.26   807.4 2223.77     857 2233.84
#Mann= 3 , 0 , 0
       0      .1       0   381.6    .045       0   395.2      .1       0
Bank Sta=381.6,395.2
XS Rating Curve= 0 ,0
Exp/Cntr=0.3,0.1

Type RM Length L Ch R = 1 ,10632.8 ,376.8,383.2,389.5
XS GIS Cut Line= 3
     1967728.895      181723.504     1967361.088      181837.398
     1966981.546      182267.522
#Sta/Elev= 30
       0 2304.09    88.8 2286.86   118.5 2286.18   177.7 2279.44   197.5 2275.63
   217.2  2269.8   246.8 2257.71   266.6 2245.68   286.3 2223.99   315.9 2202.67
   335.7 2192.08   365.3 2179.66     385 2176.41   493.8 2177.49   536.2 2173.69
   548.2 2173.35   553.2 2173.33     573 2173.99   592.7 2178.33   622.4 2189.88
     662 2201.76   711.4 2220.24   721.3 2224.38   731.2 2231.42   741.1 2236.58
     751 2239.93   790.5 2248.35   869.7 2258.76   909.2  2265.6   958.7 2284.07
#Mann= 3 , 0 , 0
       0      .1       0   536.2    .045       0   548.2      .1       0
Bank Sta=536.2,548.2
XS Rating Curve= 0 ,0
Exp/Cntr=0.3,0.1

Type RM Length L Ch R = 1 ,10249.5 ,316.7,310.1,303.5
XS GIS Cut Line= 3
      1967395.52      181432.157     1966839.307      181781.777
     1966703.092      181879.398
#Sta/Elev= 30
       0 2257.52      10 2253.68    19.9 2248.06    69.7 2235.35    99.5 2226.87
   119.4  2219.8     209 2196.52     219 2192.73   238.9 2189.56   278.7 2180.15
   318.5 2172.33   378.2 2167.47   398.2 2164.91   418.1 2156.83   424.5 2155.63
     428 2154.98   436.5  2155.6   467.8  2161.6   487.8 2168.32   507.7  2180.8
   577.3  2213.7   597.2 2217.62   617.2 2224.85   686.5 2241.37   745.7 2262.41
   765.4 2271.33   775.3 2276.91   785.1 2284.16     795 2288.47   824.6 2291.83
#Mann= 3 , 0 , 0
       0      .1       0   424.5    .045       0   436.5      .1       0
Bank Sta=424.5,436.5
XS Rating Curve= 0 ,0
Exp/Cntr=0.3,0.1

Type RM Length L Ch R = 1 ,9939    ,408.9,394.6,380.2
XS GIS Cut Line= 3
     1967157.889      181144.344     1966898.334      181361.779
     1966569.147      181756.804
#Sta/Elev= 30
       0 2209.83    39.8 2201.48   119.5 2189.96   179.3 2183.44   199.2 2183.08
   258.9 2176.76   328.6 2171.04   348.5 2167.67   358.4  2162.2   368.3 2155.28
   378.2 2150.41     388 2147.16   397.9 2146.84   399.3 2147.07   447.4 2157.23
   467.2 2159.99   506.7 2170.44   556.1 2180.35   575.9    2184   585.8 2185.12
   595.7  2184.6   625.4 2189.19   694.6 2207.96   714.4  2209.8   734.1  2215.1
   753.9 2216.74   823.1 2234.51     833 2236.34   842.9 2236.28   852.8 2238.71
#Mann= 3 , 0 , 0
       0      .1       0     388    .045       0   399.3      .1       0
Bank Sta=388,399.3
XS Rating Curve= 0 ,0
Exp/Cntr=0.3,0.1

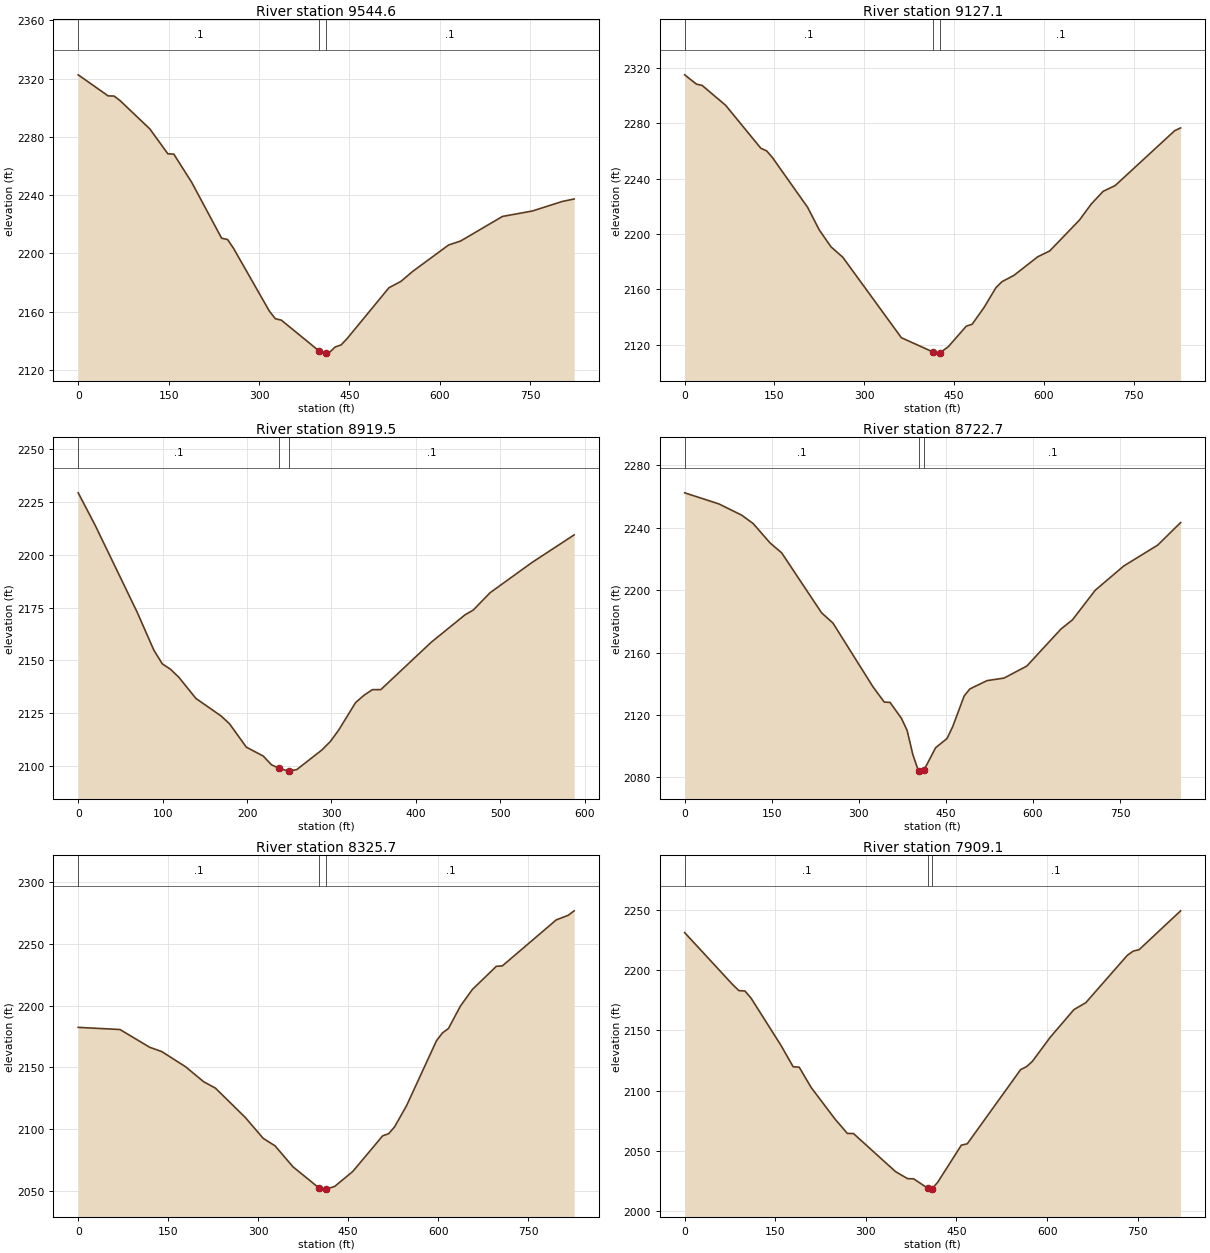
Type RM Length L Ch R = 1 ,9544.6  ,404.9,417.4,430.3
XS GIS Cut Line= 2
     1966500.218      180930.452     1966494.336       181753.12
#Sta/Elev= 30
       0 2322.57    49.6 2308.12    59.5 2307.99    69.4 2304.88   118.9 2285.38
   148.7 2268.34   158.6  2268.1   188.3  2248.7   237.9 2210.34   247.8 2209.44
   257.7 2203.36   317.2 2160.21   327.1 2155.04     337 2154.06   399.1 2133.05
   406.4 2131.41   411.1 2131.56   416.3 2131.72   426.2 2135.61   436.1 2137.05
     446 2141.35   515.4  2176.3   535.2 2180.65   555.1 2187.62   614.5  2205.7
   634.4 2208.42   703.8  2225.3   753.3 2229.02   802.9 2235.58   822.7 2237.29
#Mann= 3 , 0 , 0
       0      .1       0   399.1    .045       0   411.1      .1       0
Bank Sta=399.1,411.1
XS Rating Curve= 0 ,0
Exp/Cntr=0.3,0.1

Type RM Length L Ch R = 1 ,9127.1  ,205.9,207.5,208.8
XS GIS Cut Line= 3
     1966356.286      180874.573     1966117.859       181221.04
     1965882.198      181553.776
#Sta/Elev= 30
       0    2315    19.6  2308.3    29.3  2307.3    68.5 2292.96   127.2 2261.95
   136.9 2260.07   146.7 2255.14   205.4 2219.23     225  2202.8   244.5 2190.68
   264.1 2183.22   361.9  2125.1   414.6 2114.79   420.6 2113.95   426.6 2114.25
   440.5 2118.67   470.3 2133.42   480.2 2134.84   500.1    2147     520 2161.35
     530 2165.58   549.9 2170.11   589.6 2183.54   609.5 2187.72   659.2 2210.01
   679.1  2221.7     699 2230.87   718.9 2234.97   818.4 2274.65   828.3 2276.66
#Mann= 3 , 0 , 0
       0      .1       0   414.6    .045       0   426.6      .1       0
Bank Sta=414.6,426.6
XS Rating Curve= 0 ,0
Exp/Cntr=0.3,0.1

Type RM Length L Ch R = 1 ,8919.5  ,207,196.7,186.4
XS GIS Cut Line= 2
     1966115.095      180900.917     1965745.044      181357.239
#Sta/Elev= 30
       0 2229.43    19.9  2214.2    69.7 2172.98    89.6 2154.89    99.6 2148.38
   109.5 2145.77   119.5 2141.89   139.4    2132   169.3 2123.66   179.2 2119.99
   199.2 2108.89   219.1 2104.71     229 2100.53   237.8 2098.93   248.9 2097.54
   249.8 2097.61   258.9 2098.27   288.8 2107.61   298.7 2111.59   308.7 2117.08
   328.6 2130.03   338.6 2133.51   348.5 2136.15   358.5 2136.18   418.2 2158.62
   458.1 2171.57     468 2173.88   487.9 2182.09   537.7 2196.45   587.5  2209.5
#Mann= 3 , 0 , 0
       0      .1       0   237.8    .045       0   249.8      .1       0
Bank Sta=237.8,249.8
XS Rating Curve= 0 ,0
Exp/Cntr=0.3,0.1

Type RM Length L Ch R = 1 ,8722.7  ,397.8,396.9,398.5
XS GIS Cut Line= 3
     1965922.622      180552.919     1965810.881      181091.619
     1965625.174      181332.417
#Sta/Elev= 30
       0 2262.26      59 2255.15    98.2 2247.97   117.9 2242.62   147.4 2230.07
     167 2223.87   235.8 2185.45   255.4 2178.89   324.2 2138.16   343.8 2128.27
   353.7 2128.09   373.3 2117.95   383.2 2110.12     393 2094.72   402.8 2084.07
   412.6 2085.03   432.3 2099.07   451.9 2104.94   461.8 2112.64   481.4 2132.16
   491.2 2136.68   520.7    2142   550.2 2143.66   589.4 2151.36   648.3  2175.1
   667.9 2180.89   707.1 2199.84   756.2 2215.38     815 2228.84   854.3 2243.22
#Mann= 3 , 0 , 0
       0      .1       0   402.8    .045       0   412.6      .1       0
Bank Sta=402.8,412.6
XS Rating Curve= 0 ,0
Exp/Cntr=0.3,0.1

Type RM Length L Ch R = 1 ,8325.7  ,420.6,416.5,411.3
XS GIS Cut Line= 3
      1965554.12      180389.212     1965487.708      180791.463
     1965373.212      181194.504
#Sta/Elev= 30
       0 2182.52    69.6 2180.77   119.3 2166.34   139.2 2162.91     179 2150.58
   208.8 2138.55   228.7 2133.28   278.4 2109.53   308.3 2092.57   328.2 2086.43
     358 2069.49   401.7 2052.19   407.7 2051.38   413.7 2051.39   427.6 2053.62
   457.6 2065.65   507.5 2094.59   517.4  2096.3   527.4 2101.88   547.4  2119.1
   597.2 2171.67   607.2 2178.04   617.2 2181.62   637.1 2199.78   657.1 2213.27
     697    2232     707 2232.34   796.8 2269.63   816.7 2273.35   826.7 2276.99
#Mann= 3 , 0 , 0
       0      .1       0   401.7    .045       0   413.7      .1       0
Bank Sta=401.7,413.7
XS Rating Curve= 0 ,0
Exp/Cntr=0.3,0.1

Type RM Length L Ch R = 1 ,7909.1  ,396.5,400,401.8
XS GIS Cut Line= 3
     1965072.157      180330.682     1965096.754      180738.987
     1965079.727      181150.708
#Sta/Elev= 30
       0 2231.47    79.8 2188.02    89.8  2183.2    99.8 2182.85   109.7 2177.09
   159.6 2137.45   179.6  2119.8   189.6 2119.44   209.5 2102.46   249.4 2075.94
   269.4 2064.26   279.4 2064.21   349.2 2032.44   369.1 2026.62   379.1 2026.49
     403 2018.49     409  2017.9   418.9 2023.59   458.1 2054.52   467.9 2055.65
   556.2 2117.39     566 2119.87   575.8 2124.37   605.3  2144.4   644.5 2167.39
   664.1 2173.13   732.8 2212.55   742.6 2216.07   752.4 2217.28   821.1 2249.62
#Mann= 3 , 0 , 0
       0      .1       0     403    .045       0     409      .1       0
Bank Sta=403,409
XS Rating Curve= 0 ,0
Exp/Cntr=0.3,0.1

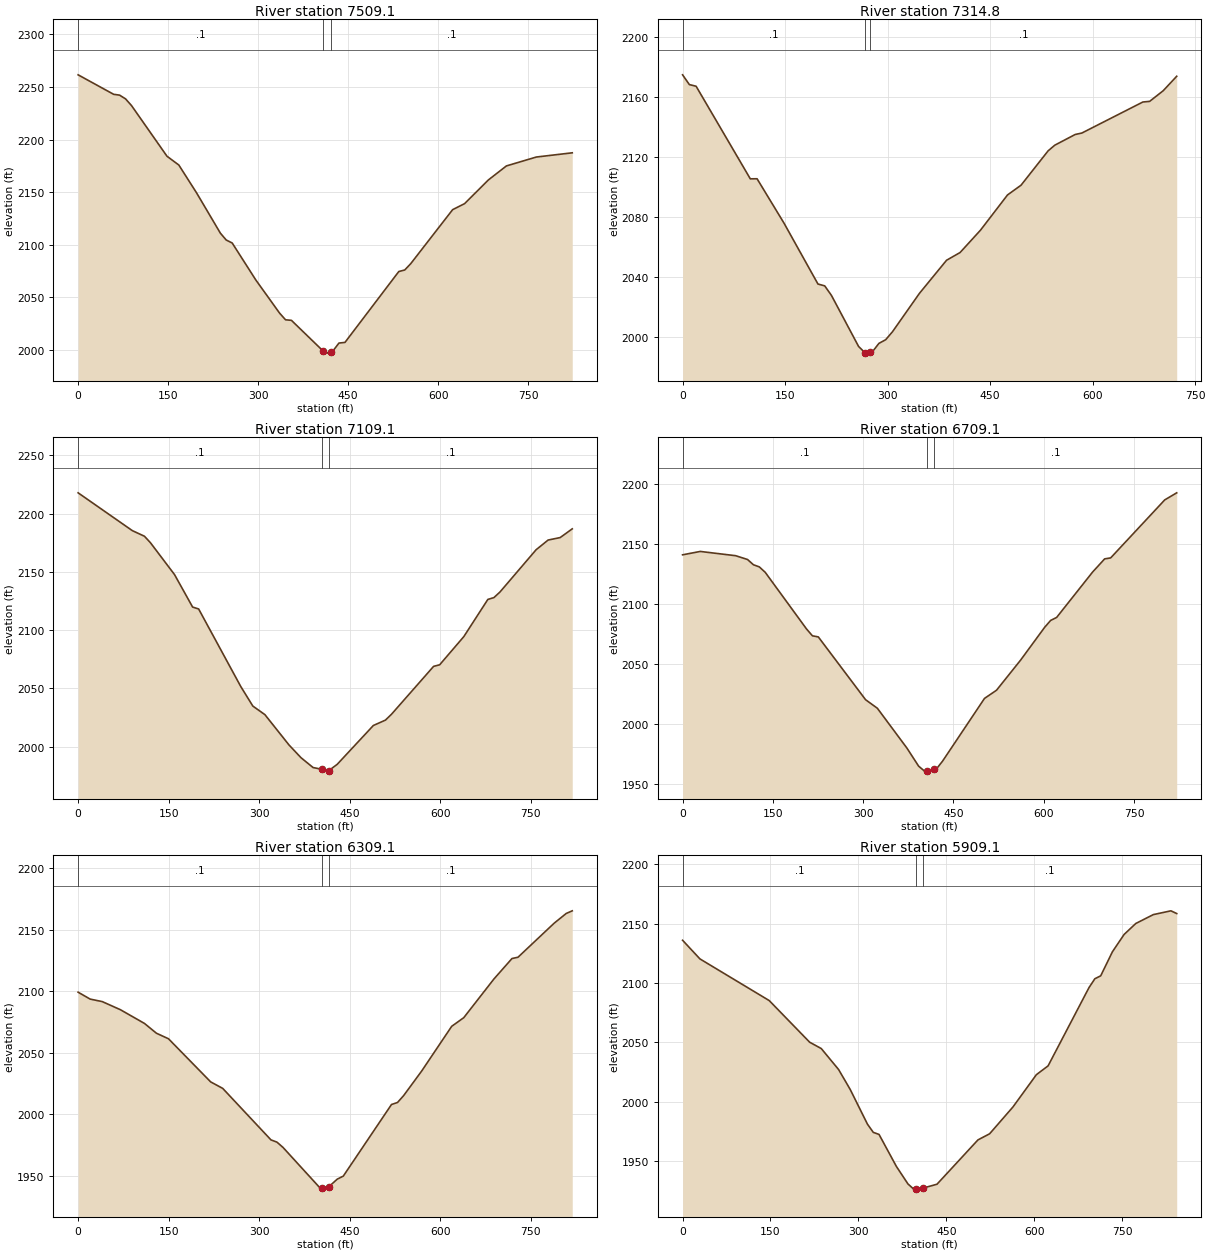
Type RM Length L Ch R = 1 ,7509.1  ,200,194.3,188.7
XS GIS Cut Line= 3
     1964757.689      180358.166     1964700.961       180768.94
     1964649.376      181174.258
#Sta/Elev= 30
       0  2261.5    59.2 2242.99    69.1  2242.2      79 2238.68    88.9 2232.34
   148.1 2184.16   167.8 2175.82   197.5 2149.26     237 2111.12   246.8 2104.58
   256.7 2101.76   296.2 2066.54   335.7 2035.14   345.6  2028.8   355.4  2028.3
   408.7  1998.9   414.7 1997.15   420.7 1998.42   424.6 1999.24   434.6 2006.71
   444.6 2007.32   534.3 2074.65   544.2 2076.12   554.2 2082.13     624 2133.42
   643.9 2139.13   683.7 2161.71   713.6 2174.96   763.5 2183.42   823.3 2187.42
#Mann= 3 , 0 , 0
       0      .1       0   408.7    .045       0   420.7      .1       0
Bank Sta=408.7,420.7
XS Rating Curve= 0 ,0
Exp/Cntr=0.3,0.1

Type RM Length L Ch R = 1 ,7314.8  ,209.3,205.7,202.4
XS GIS Cut Line= 2
      1964475.97      180501.352      1964566.78      181218.753
#Sta/Elev= 30
       0 2174.74     9.9 2168.23    19.8 2167.12    99.1 2105.35     109  2105.4
   148.6 2075.65   198.1 2035.17     208 2033.94   217.9 2027.53   257.6  1993.5
   267.5 1989.07   274.6 1989.55   277.4 1989.74   287.3 1995.57   297.2 1998.02
   307.1  2003.3   346.7    2029   386.3 2051.03   406.1 2056.19   435.9 2071.07
   475.5  2094.6   495.3  2101.1   534.9 2124.01   544.8 2127.83   574.5 2134.93
   584.4 2135.92   673.6 2156.61   683.5 2157.03   703.3 2164.12   723.1 2173.78
#Mann= 3 , 0 , 0
       0      .1       0   267.5    .045       0   274.6      .1       0
Bank Sta=267.5,274.6
XS Rating Curve= 0 ,0
Exp/Cntr=0.3,0.1

Type RM Length L Ch R = 1 ,7109.1  ,400.1,400,401
XS GIS Cut Line= 3
     1964187.236      180417.089     1964308.607       180808.17
     1964421.884      181201.802
#Sta/Elev= 30
       0 2217.88    89.9 2185.42   109.9 2180.64   119.8 2175.12   159.8 2147.72
   189.8 2119.84   199.8 2118.19   269.7 2051.57   289.6 2034.88   309.6 2027.53
   349.6 2001.48   369.5 1990.54   389.5 1982.11   403.5 1980.65   409.5 1979.03
   415.5 1979.46   429.5 1984.87   489.4 2018.19   509.4  2022.8   519.4  2027.8
   589.3 2068.95   599.3 2070.28   639.3 2094.43   679.2 2126.39   689.2 2127.95
   699.2  2132.7   759.2 2169.03   779.1 2177.35   799.1 2179.48   819.1 2186.96
#Mann= 3 , 0 , 0
       0      .1       0   403.5    .045       0   415.5      .1       0
Bank Sta=403.5,415.5
XS Rating Curve= 0 ,0
Exp/Cntr=0.3,0.1

Type RM Length L Ch R = 1 ,6709.1  ,387,399.9,411.4
XS GIS Cut Line= 3
     1963824.617      180584.878     1963948.399      180977.671
     1964043.151      181375.635
#Sta/Elev= 30
       0 2140.73    29.4 2143.54    88.2 2139.99   107.9 2136.83   117.7 2132.46
   127.5 2130.66   137.3 2126.16   205.9 2079.03   215.7 2073.34   225.5 2072.41
     304 2020.17   323.6 2013.05   372.6 1979.99   392.2 1964.84     402 1960.74
   405.8 1961.15   417.8 1962.31   421.8 1962.64   431.8 1968.97   501.6 2021.25
   521.6 2028.07   561.5 2053.08   601.4 2080.33   611.4 2086.12   621.4 2088.61
   681.2 2126.41   701.2 2137.35   711.2 2138.17     801 2186.42   820.9 2192.31
#Mann= 3 , 0 , 0
       0      .1       0   405.8    .045       0   417.8      .1       0
Bank Sta=405.8,417.8
XS Rating Curve= 0 ,0
Exp/Cntr=0.3,0.1

Type RM Length L Ch R = 1 ,6309.1  ,405.1,400,397.9
XS GIS Cut Line= 3
       1963680.9      180573.326     1963556.506      180963.475
     1963432.111      181353.624
#Sta/Elev= 30
       0 2099.12      20 2093.51      40 2091.49    69.9 2084.95   109.9 2073.78
   129.8 2065.81   149.8 2061.31   219.7  2026.3   239.7 2021.01   319.6 1979.23
   329.6 1977.37   339.6 1973.09   399.5 1940.97   403.5 1940.27   409.5 1939.23
   415.5 1941.16   429.5 1947.33   439.5 1949.79   519.4 2007.93   529.4 2009.58
   539.3 2015.01   569.3 2035.02   619.2 2071.42   639.2 2078.44   689.2 2109.85
   719.1 2126.45   729.1 2127.51     789 2155.14     809 2163.04     819 2165.19
#Mann= 3 , 0 , 0
       0      .1       0   403.5    .045       0   415.5      .1       0
Bank Sta=403.5,415.5
XS Rating Curve= 0 ,0
Exp/Cntr=0.3,0.1

Type RM Length L Ch R = 1 ,5909.1  ,185.1,180.1,171.9
XS GIS Cut Line= 3
     1963244.866      180376.972     1963213.859      180780.069
     1963116.347      181208.143
#Sta/Elev= 30
       0 2135.94    29.6 2120.24   147.9 2085.12   216.9 2050.05   236.7 2044.71
   266.2 2027.08     286 2010.32   315.5 1981.05   325.4 1974.13   335.3 1972.35
   364.8 1945.49   384.6 1930.68   394.4 1926.29   398.3 1926.31   410.3 1927.14
   434.2 1930.43   504.1 1967.76     524 1972.91   563.9 1995.55   603.8  2022.7
   623.8 2030.14   693.6 2096.05   703.6 2103.53   713.6    2106   733.6 2126.25
   753.5 2140.83   773.5 2150.08   803.4 2157.56   833.4 2160.74   843.3 2158.45
#Mann= 3 , 0 , 0
       0      .1       0   398.3    .045       0   410.3      .1       0
Bank Sta=398.3,410.3
XS Rating Curve= 0 ,0
Exp/Cntr=0.3,0.1

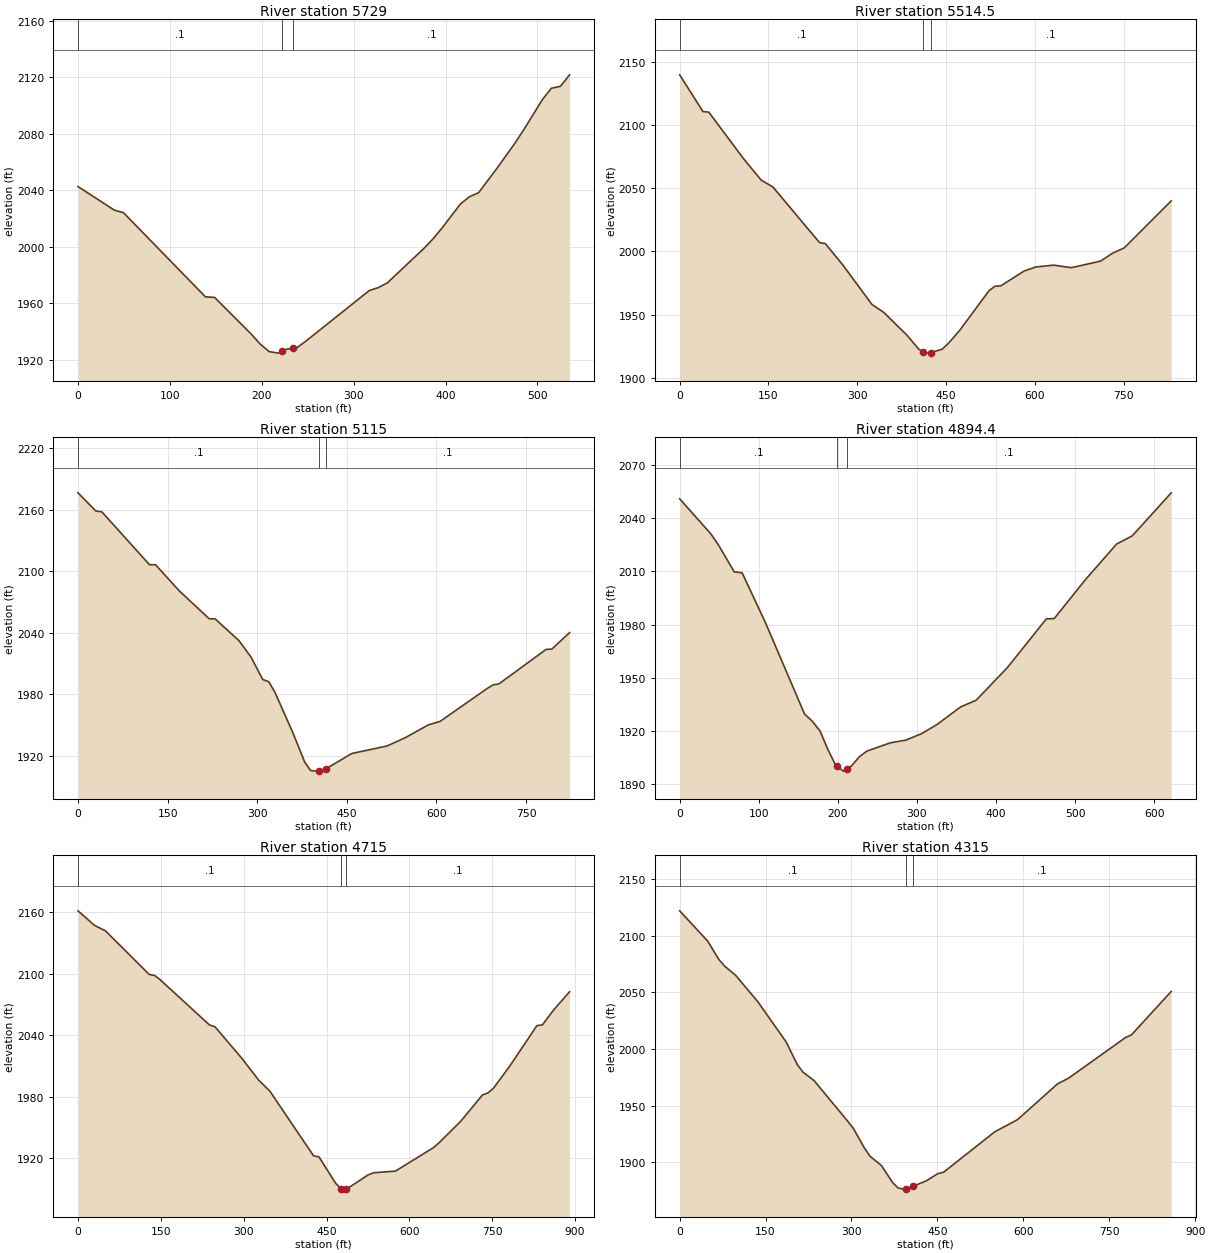
Type RM Length L Ch R = 1 ,5729    ,206,214.4,225.5
XS GIS Cut Line= 2
     1963000.586      180562.933     1963087.424      181090.767
#Sta/Elev= 30
       0 2042.61    39.6  2025.9    49.5 2024.09   138.7 1964.42   148.6 1964.06
   188.2 1938.29   198.1 1931.09     208 1925.63   217.9 1924.55   222.3 1925.84
   227.8 1927.45   234.3 1927.94   237.8 1928.21   247.6 1932.87     317 1968.91
   326.9 1971.04   336.8 1974.42   376.4 1998.73   386.3  2005.5   396.2 2013.24
   416.1 2030.23     426  2035.4   435.9 2038.25   455.7 2055.33   475.5 2073.38
   485.4  2083.2   505.2 2104.13   515.1 2112.29     525 2113.65   534.9  2121.8
#Mann= 3 , 0 , 0
       0      .1       0   222.3    .045       0   234.3      .1       0
Bank Sta=222.3,234.3
XS Rating Curve= 0 ,0
Exp/Cntr=0.3,0.1

Type RM Length L Ch R = 1 ,5514.5  ,401.7,399.5,392.5
XS GIS Cut Line= 3
     1962924.062      180370.869     1962824.576      180782.419
     1962663.207      181156.112
#Sta/Elev= 30
       0 2139.65    39.4 2110.59    49.2 2110.14   108.3  2073.1   137.8 2056.35
   157.6 2050.88   236.3 2006.94   246.2  2006.1   275.7  1989.2   324.9 1957.98
   344.6 1951.82     384 1933.69   403.7 1922.81   411.9 1920.08   413.6 1919.51
   423.9 1919.98   443.3 1922.58   453.2 1926.84     473 1937.46   522.7 1968.95
   532.6 1972.41   542.5 1972.69   582.2 1984.55   602.1 1987.69   631.9  1989.1
   661.7 1987.09   711.3 1992.32   731.2 1998.54     751 2002.73   830.4 2039.94
#Mann= 3 , 0 , 0
       0      .1       0   411.9    .045       0   423.9      .1       0
Bank Sta=411.9,423.9
XS Rating Curve= 0 ,0
Exp/Cntr=0.3,0.1

Type RM Length L Ch R = 1 ,5115    ,229.3,220.5,213.9
XS GIS Cut Line= 3
      1962497.58      180291.391     1962440.443      180696.504
     1962425.484      181109.826
#Sta/Elev= 30
       0 2176.67    29.9 2158.94    39.9 2158.17   119.7 2106.52   129.7 2106.56
   169.6 2081.02   219.5 2053.91   229.5 2053.74   269.4 2032.52   289.4 2016.67
   309.3 1994.55   319.3  1992.4   329.3 1982.47   359.2 1943.34   379.2 1914.39
   389.2 1905.81   399.1 1905.26   403.1 1905.44   415.1 1907.55   458.4 1922.49
   517.4 1929.79     547 1937.65   586.4 1950.36   606.1  1953.8   684.8 1985.86
   694.7 1989.35   704.6 1990.37   783.3 2023.92   793.2 2024.35   822.7 2040.34
#Mann= 3 , 0 , 0
       0      .1       0   403.1    .045       0   415.1      .1       0
Bank Sta=403.1,415.1
XS Rating Curve= 0 ,0
Exp/Cntr=0.3,0.1

Type RM Length L Ch R = 1 ,4894.4  ,166.4,179.4,192.9
XS GIS Cut Line= 2
     1962173.078      180533.987     1962343.347      181131.632
#Sta/Elev= 30
       0 2050.87    39.5 2031.07    49.3 2024.71      69 2009.68    78.9 2009.22
   108.5 1981.08   157.8 1929.73   167.7  1925.6   177.6 1920.02   187.4 1909.69
   197.3 1900.79   199.2 1900.16   207.1 1897.52   211.2 1898.68     217 1900.31
   226.9 1905.49   236.7 1908.81   266.3 1913.45     286    1915   305.8 1918.61
   325.5 1923.82   355.1 1933.65   374.8 1937.44   414.3 1955.81   463.6 1983.25
   473.5 1983.42   512.9 2005.31   552.4 2025.39   572.1 2029.97   621.4 2054.21
#Mann= 3 , 0 , 0
       0      .1       0   199.2    .045       0   211.2      .1       0
Bank Sta=199.2,211.2
XS Rating Curve= 0 ,0
Exp/Cntr=0.3,0.1

Type RM Length L Ch R = 1 ,4715    ,391.3,399.9,403
XS GIS Cut Line= 3
     1962215.736      180286.588     1962053.768       180755.42
     1961916.024      181124.655
#Sta/Elev= 30
       0 2161.51    29.8 2147.34    49.6 2142.01     129 2099.37   138.9 2098.35
   148.8 2094.23   238.1 2050.08     248 2048.31   297.6 2016.92   327.4 1996.04
   347.2 1985.65   426.6 1922.29   436.5  1921.2   466.3 1895.65   476.2 1890.22
   486.1 1889.79   525.6 1903.75   535.4 1905.79   574.8 1907.38   643.8 1930.37
   653.7 1934.96   693.1 1956.09   732.5 1981.78   742.3 1983.74   752.2  1988.2
   781.7  2009.8     831 2049.43   840.8  2050.1   860.6 2064.24   890.1 2082.49
#Mann= 3 , 0 , 0
       0      .1       0   476.2    .045       0   486.1      .1       0
Bank Sta=476.2,486.1
XS Rating Curve= 0 ,0
Exp/Cntr=0.3,0.1

Type RM Length L Ch R = 1 ,4315    ,419.6,421.6,428.7
XS GIS Cut Line= 3
     1962064.014      180157.394     1961798.077      180457.648
     1961585.078      180862.138
#Sta/Elev= 30
       0 2122.07    48.9  2095.4    68.5  2079.1    78.3 2073.38    97.8 2065.13
     137 2041.51   185.9 2006.37   205.4 1986.33   215.2 1979.78   234.8 1972.19
   293.5 1936.34   303.3 1930.04   322.8 1912.52   332.6 1905.37   352.2 1897.33
   371.7 1882.32   381.5 1877.44   391.3 1876.46   395.1 1876.93   407.1 1878.85
   430.9 1883.82   450.8 1890.16   460.7 1891.33   550.2 1927.07   589.9 1937.78
   659.5 1969.26   679.4 1974.52   778.7 2010.33   788.7 2012.52   858.2 2050.92
#Mann= 3 , 0 , 0
       0      .1       0   395.1    .045       0   407.1      .1       0
Bank Sta=395.1,407.1
XS Rating Curve= 0 ,0
Exp/Cntr=0.3,0.1