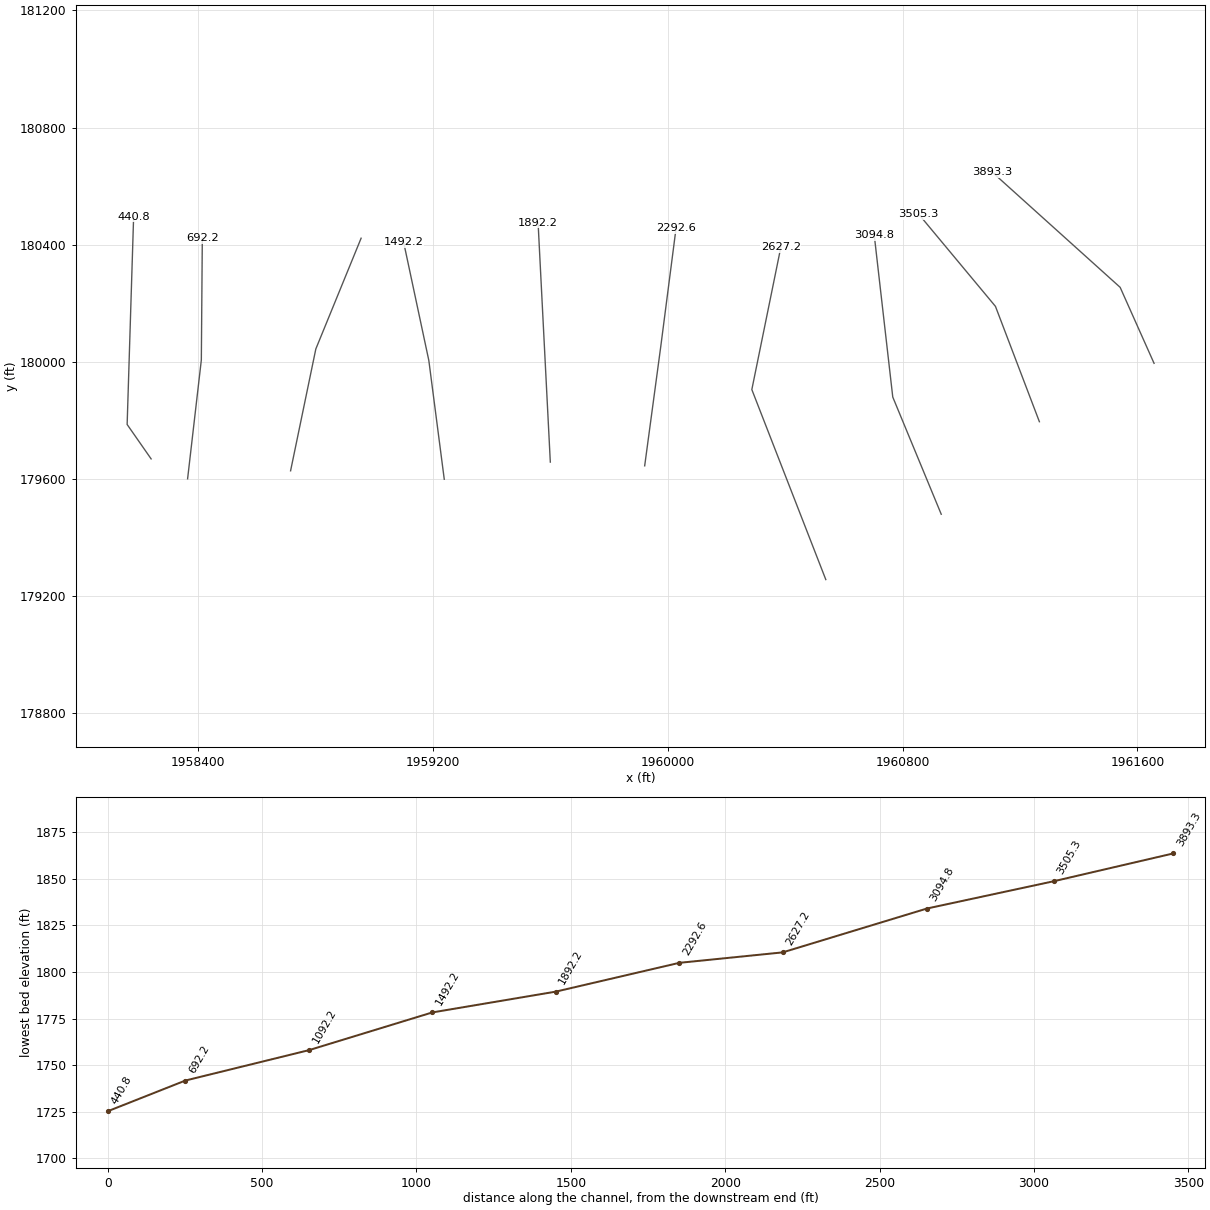
HEC-RAS study IndnBrnch.prj: IndnBrnch

--- IndnBrnch.g01 (geometry) --- (continued)

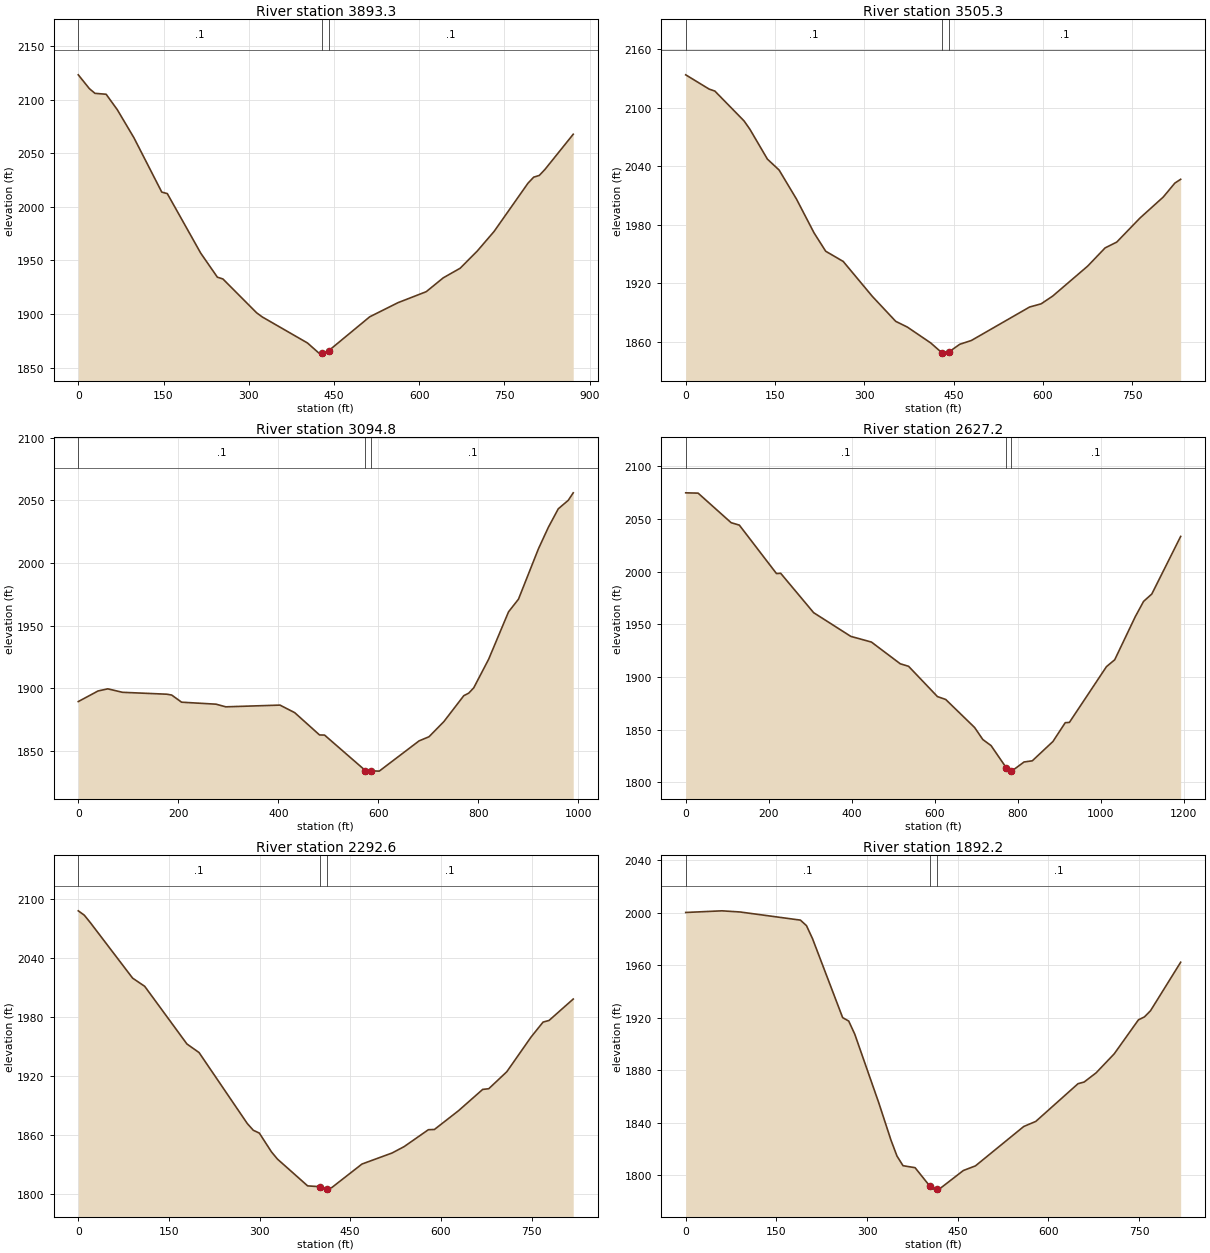
Type RM Length L Ch R = 1 ,3893.3  ,393.2,387.8,384.6
XS GIS Cut Line= 3
     1961656.937      179995.297     1961541.379      180254.745
     1961105.489      180648.067
#Sta/Elev= 30
       0    2123    19.6 2110.08    29.4 2105.74      49  2104.9    68.6 2090.54
    97.9 2064.37   146.9  2013.7   156.7 2012.26   215.5 1956.77   244.8 1934.37
   254.6 1932.68   313.9 1901.15   323.8  1897.3   403.4 1873.02   423.3 1863.69
     429 1863.62   433.3 1863.57     441 1865.96   512.9 1897.42   562.6 1910.58
   612.4 1920.85   642.3 1933.74   672.1 1942.71     702 1958.62   731.8    1977
   791.5    2022   801.5  2027.6   811.4 2029.22   821.4 2034.85   871.1 2067.61
#Mann= 3 , 0 , 0
       0      .1       0     429    .045       0     441      .1       0
Bank Sta=429,441
XS Rating Curve= 0 ,0
Exp/Cntr=0.3,0.1

Type RM Length L Ch R = 1 ,3505.3  ,420.7,410.4,397.9
XS GIS Cut Line= 3
     1961266.203      179795.966      1961116.55      180189.748
     1960854.542      180505.125
#Sta/Elev= 30
       0 2133.77    39.2  2119.2      49 2117.09      98 2086.54   107.8 2077.98
   137.2  2047.4   156.8 2036.26   186.1 2006.41   215.5 1971.87   235.1 1953.04
   264.5 1942.58   313.5 1906.74   352.7 1881.21   372.3 1875.31   411.5 1859.08
     430 1849.14     431 1848.64     442 1849.81   460.3 1857.72   479.8  1861.6
   577.5 1895.86     597 1899.16   616.5 1907.15   675.1 1937.78   704.4 1956.46
   723.9 1962.38   762.9    1987     802 2008.52   821.5 2022.82   831.3 2026.74
#Mann= 3 , 0 , 0
       0      .1       0     430    .045       0     442      .1       0
Bank Sta=430,442
XS Rating Curve= 0 ,0
Exp/Cntr=0.3,0.1

Type RM Length L Ch R = 1 ,3094.8  ,474.5,467.6,460.7
XS GIS Cut Line= 3
     1960931.815       179480.02     1960766.653      179880.153
     1960703.466      180433.641
#Sta/Elev= 30
       0 1889.51    39.4 1897.94      59 1899.66    88.5 1896.89   177.1 1895.38
   186.9  1894.7   206.6 1889.01   275.5 1887.42   295.1 1885.31   403.4 1886.69
   432.9 1880.66   482.6 1862.87   492.6 1862.78   574.2 1834.49   586.2 1834.23
     602 1834.02   681.6 1858.13   701.5 1861.44   731.3 1873.55   771.1  1894.2
   781.1 1896.27     791 1900.48   820.8 1923.27   860.6 1961.08   880.5  1971.2
   920.3 2011.28   940.2 2028.48   960.1 2043.28     980 2050.02     990 2056.02
#Mann= 3 , 0 , 0
       0      .1       0   574.2    .045       0   586.2      .1       0
Bank Sta=574.2,586.2
XS Rating Curve= 0 ,0
Exp/Cntr=0.3,0.1

Type RM Length L Ch R = 1 ,2627.2  ,333,334.6,336.2
XS GIS Cut Line= 3
     1960538.493      179256.967     1960286.494      179905.693
     1960385.441      180392.325
#Sta/Elev= 30
       0 2074.95    29.8 2074.66   109.4 2046.58   129.2 2044.26   218.7 1998.21
   228.7 1998.53   308.2 1961.06   397.7 1938.55   447.4 1933.14     517 1912.48
   536.9 1910.12   606.5 1881.32   626.4 1878.59     696 1851.97   715.8 1840.53
   735.7 1834.75   772.8 1813.39   784.8 1810.57   785.3 1810.49   815.1 1819.18
     835 1820.28   884.7 1838.62   914.4 1856.53   924.4 1856.78  1013.8 1909.82
  1033.6 1916.32  1083.3 1957.39  1103.2 1971.81    1123 1978.81  1192.5 2033.53
#Mann= 3 , 0 , 0
       0      .1       0   772.8    .045       0   784.8      .1       0
Bank Sta=772.8,784.8
XS Rating Curve= 0 ,0
Exp/Cntr=0.3,0.1

Type RM Length L Ch R = 1 ,2292.6  ,396.6,400.4,404.1
XS GIS Cut Line= 3
     1959921.423      179645.277     1959976.012       180051.13
     1960028.416      180457.261
#Sta/Elev= 30
       0 2088.14      10 2083.67      20 2076.07    89.9 2019.63   109.9 2011.31
   179.8  1952.6   199.8 1943.92   279.7 1871.62   289.6 1864.79   299.6 1861.92
   319.6 1842.85   329.6 1835.45   379.5  1808.2   399.8 1807.37   409.5 1804.89
   411.8 1805.26   419.5 1806.48   469.4 1830.42   519.4  1841.7   539.4 1848.24
   579.3 1865.36   589.3 1865.61   629.2 1884.71   669.2 1906.39   679.2 1907.07
   709.1 1924.38   749.1 1959.58   769.1 1974.91     779 1976.56     819 1998.35
#Mann= 3 , 0 , 0
       0      .1       0   399.8    .045       0   411.8      .1       0
Bank Sta=399.8,411.8
XS Rating Curve= 0 ,0
Exp/Cntr=0.3,0.1

Type RM Length L Ch R = 1 ,1892.2  ,398.4,400,403.3
XS GIS Cut Line= 3
     1959599.913      179658.067     1959579.047      180067.035
     1959558.181      180476.003
#Sta/Elev= 30
       0 2000.16    59.9 2001.42    89.9 2000.54   189.8 1994.34   199.8 1990.14
   209.7 1980.36   259.7 1920.05   269.7 1917.47   279.7  1907.5   319.6 1854.98
   339.6 1826.82   349.6 1814.62   359.6 1807.28   379.5 1805.78   403.5 1791.99
   409.5 1789.51   415.5 1789.47   419.5 1789.44   459.4 1803.62   479.4 1807.14
   559.3 1837.14   579.3 1841.03   649.2 1869.76   659.2    1871   679.2 1878.06
   709.1 1892.52   749.1 1918.38   759.1 1920.64   769.1 1925.32     819 1962.26
#Mann= 3 , 0 , 0
       0      .1       0   403.5    .045       0   415.5      .1       0
Bank Sta=403.5,415.5
XS Rating Curve= 0 ,0
Exp/Cntr=0.3,0.1

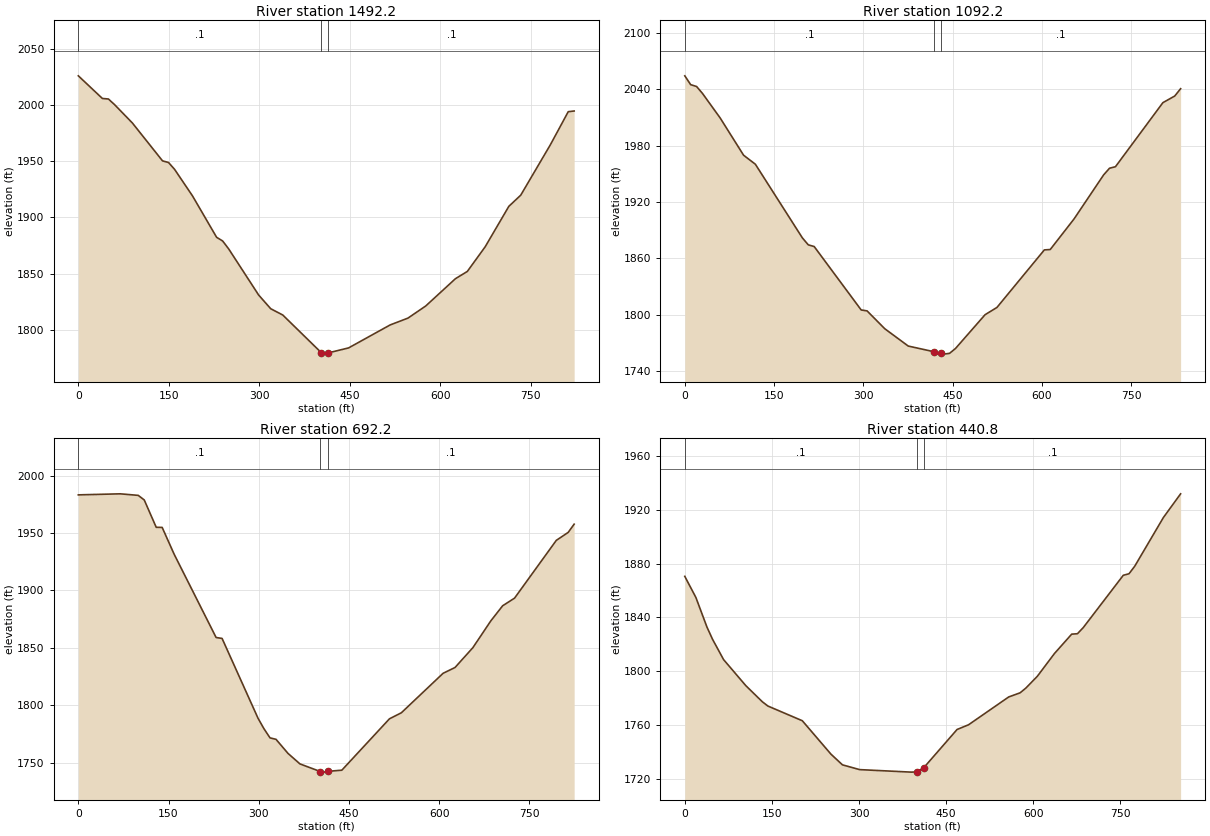
Type RM Length L Ch R = 1 ,1492.2  ,406.7,399.7,387
XS GIS Cut Line= 3
     1959238.574      179599.512     1959186.019      180004.935
      1959100.04      180409.273
#Sta/Elev= 30
       0 2026.21    39.9 2006.03    49.9 2005.56    59.8 2000.71    89.7 1984.15
   139.6 1950.46   149.6 1948.98   159.5 1942.98   189.4 1919.18   229.3 1882.36
   239.3  1879.1   249.3 1872.04   299.1 1830.87   319.1 1818.69     339 1813.14
   402.8 1779.64   408.8 1778.28   414.8 1779.43   448.2 1783.83   517.1 1804.29
   546.6 1810.36   576.1 1821.18   625.4 1845.51     645 1851.92   674.6 1873.86
   713.9 1909.94   733.6 1919.88   782.8 1964.83   812.4 1994.26   822.2 1994.87
#Mann= 3 , 0 , 0
       0      .1       0   402.8    .045       0   414.8      .1       0
Bank Sta=402.8,414.8
XS Rating Curve= 0 ,0
Exp/Cntr=0.3,0.1

Type RM Length L Ch R = 1 ,1092.2  ,398.5,400.1,408
XS GIS Cut Line= 3
     1958714.975      179628.294     1958801.021      180044.375
     1958955.291       180422.48
#Sta/Elev= 30
       0 2054.46     9.9 2045.04    19.8 2043.09    29.6 2035.81    59.3 2009.71
    98.8  1969.9   118.6 1960.29   197.6 1881.84   207.5 1874.44   217.4 1872.66
   296.4 1805.09   306.3  1804.1     336 1785.12   375.5 1766.64   418.9 1760.58
   430.9 1758.73   434.8 1758.05   444.8 1758.85   454.8 1763.99   504.6 1800.04
   524.5 1807.74   604.2 1869.05   614.1 1869.46     654 1901.94   703.8 1948.92
   713.7 1956.04   723.7 1957.65   803.4 2025.88   823.3 2032.94   833.2 2040.77
#Mann= 3 , 0 , 0
       0      .1       0   418.9    .045       0   430.9      .1       0
Bank Sta=418.9,430.9
XS Rating Curve= 0 ,0
Exp/Cntr=0.3,0.1

Type RM Length L Ch R = 1 ,692.2   ,249.6,251.4,250.9
XS GIS Cut Line= 3
     1958364.114      179601.022      1958410.92      180006.674
     1958414.261      180422.711
#Sta/Elev= 30
       0 1983.18    69.7 1984.09    99.6 1982.74   109.6 1978.75   129.5 1954.95
   139.4 1954.84   159.4 1931.41   229.1 1858.97     239 1858.18   298.8 1788.65
   308.8 1779.42   318.7 1771.59   328.7 1770.31   348.6 1758.07   368.5 1748.91
   402.3 1742.29   408.3 1741.76   414.3 1742.43   438.1 1743.43   517.3 1788.18
   537.1 1793.44   606.5 1827.82   626.3 1832.86     656 1850.13   685.7 1873.36
   705.5 1886.61   725.3 1893.27   794.7 1943.56   814.5 1950.51   824.4 1957.67
#Mann= 3 , 0 , 0
       0      .1       0   402.3    .045       0   414.3      .1       0
Bank Sta=402.3,414.3
XS Rating Curve= 0 ,0
Exp/Cntr=0.3,0.1

Type RM Length L Ch R = 1 ,440.8   ,429,440.7,452.3
XS GIS Cut Line= 3
     1958239.857      179669.019     1958158.128      179786.505
     1958180.263      180496.528
#Sta/Elev= 30
       0  1870.5    19.1 1854.84    38.2 1832.84    47.7 1823.89    66.8 1808.75
     105 1789.46   133.6 1777.44   143.1 1774.31   202.3 1763.41   251.6 1738.63
   271.4  1730.7     301 1727.16   389.8  1725.3   399.6 1725.43   411.6  1728.7
   468.7 1756.93   488.4 1760.41   557.5 1781.04   577.2 1784.13   587.1 1787.64
   606.8 1796.35   636.4 1813.32     666 1827.64   675.9 1827.96   685.8 1832.45
   754.8  1871.3   764.7 1872.45   774.6  1878.1   823.9 1914.18   853.5 1931.72
#Mann= 3 , 0 , 0
       0      .1       0   399.6    .045       0   411.6      .1       0
Bank Sta=399.6,411.6
XS Rating Curve= 0 ,0
Exp/Cntr=0.3,0.1

Chan Stop Cuts=-1
Use User Specified Reach Order=0
Composite Channel Slope=5